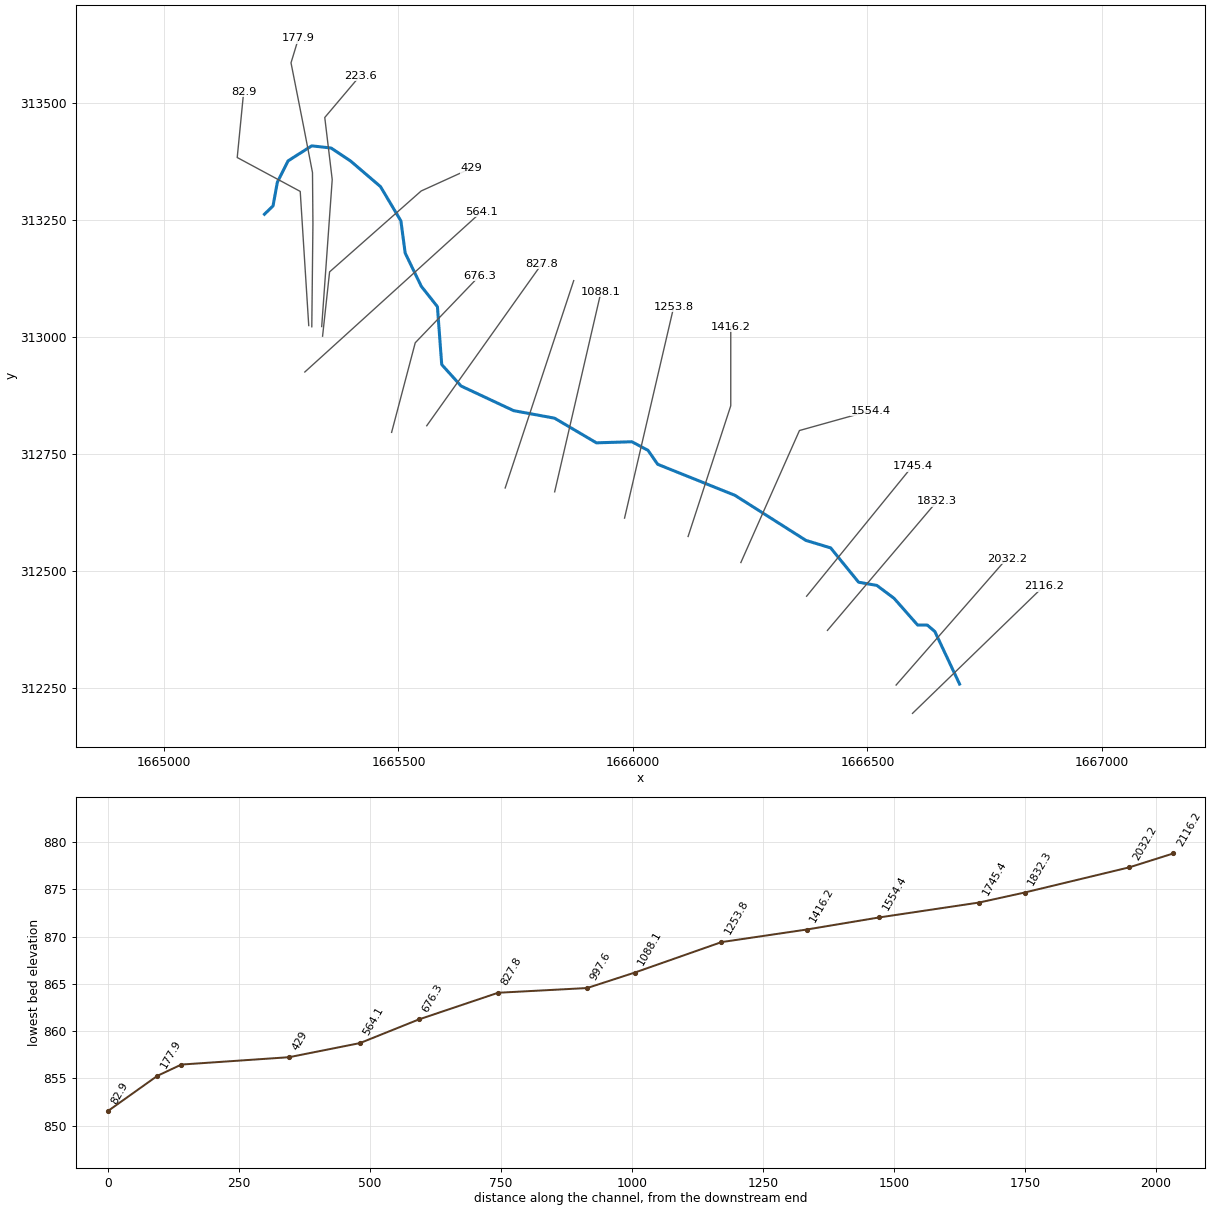
--- ELKHORNRN.prj (project) ---

Proj Title=ELKHORNRN
Current Plan=p01
Geom File=g01
Flow File=f01
Plan File=p01
DSS Export Rating Curves=0
DSS Export Rating Curve Sorted=0
DSS Export Volume Flow Curves=0
DXF OffsetX=0
DXF OffsetY=0
DXF ScaleX=0
DXF ScaleY=0

--- ELKHORNRN.p01 (plan) ---

Plan Title=Floodplain
Program Version=4.00
Geom File=g01
Flow File=f01
K Sum by GR=0
Std Step Tol=0.01
Critical Tol=0.01
Num of Std Step Trials=20
Max Error Tol=0.3
Flow Tol Ratio=0.001
Split Flow NTrial=30
Split Flow Tol=0.02
Split Flow Ratio=0.02
Log Output Level=0
Friction Slope Method=1
Unsteady Friction Slope Method=2
Unsteady Bridges Friction Slope Method=1
Global Log Level=0
CheckData=False
Run HTab=0
Run UNet=0
Run PostProcess=0
UNET Theta=0
UNET Theta Warmup=0
UNET ZTol=0
UNET ZSATol=0
UNET MxIter=0
UNET MaxInSteps=0
UNET DtIC=0
UNET DtMin=0
UNET MaxCRTS=0
UNET WFStab=0
UNET SFStab=0
UNET WFX=0
UNET SFX=0
UNET DSS MLevel=0
UNET DZMax Abort=0
UNET Convert EG Bridges=0
UNET Use Existing IB Tables=0
UNET Froude Limit=0
UNET Froude Power=0
Write IC File=0
Echo Input=False
Echo Output=False
Write Detailed=0

--- ELKHORNRN.f01 (steady flow) ---

Flow Title=NFF Regression Equation
Program Version=4.10
Number of Profiles= 1
Profile Names=P100yr
River Rch & RM=ELKHORNRN,Main            ,2116.2
585.5017
River Rch & RM=ELKHORNRN,Main            ,564.1
645.7864
River Rch & RM=ELKHORNRN,Main            ,223.6
647.7281
Boundary for River Rch & Prof#=ELKHORNRN,Main            , 1
Up Type= 0
Dn Type= 3
Dn Slope=0.03965
DSS Import GetInterval= 0
DSS Import GetPeak= 0
DSS Import FillOption= 0

--- ELKHORNRN.g01 (geometry) ---

Geom Title=USGS 10m DEM
Program Version=4.10

River Reach=ELKHORNRN       ,Main
Reach XY= 30
     1666696.541      312258.431     1666643.849      312370.687
     1666627.813      312384.432     1666607.194      312384.432
     1666556.793      312441.706     1666520.138      312469.197
     1666481.192       312476.07     1666421.628       312549.38
     1666368.936      312565.417     1666217.734      312661.636
     1666052.787      312728.073     1666032.168      312757.856
     1665997.804      312776.183     1665922.203      312773.892
     1665832.856      312826.584       1665745.8       312842.62
     1665633.544      312895.312     1665592.307      312941.131
     1665583.143      313064.842     1665548.779      313108.369
     1665514.415      313179.389     1665505.252      313248.117
     1665461.724      313321.427     1665397.577       313376.41
      1665356.34      313403.901     1665315.103      313408.483
     1665264.703       313376.41     1665241.793      313330.591
     1665232.629       313280.19     1665214.288      313262.342

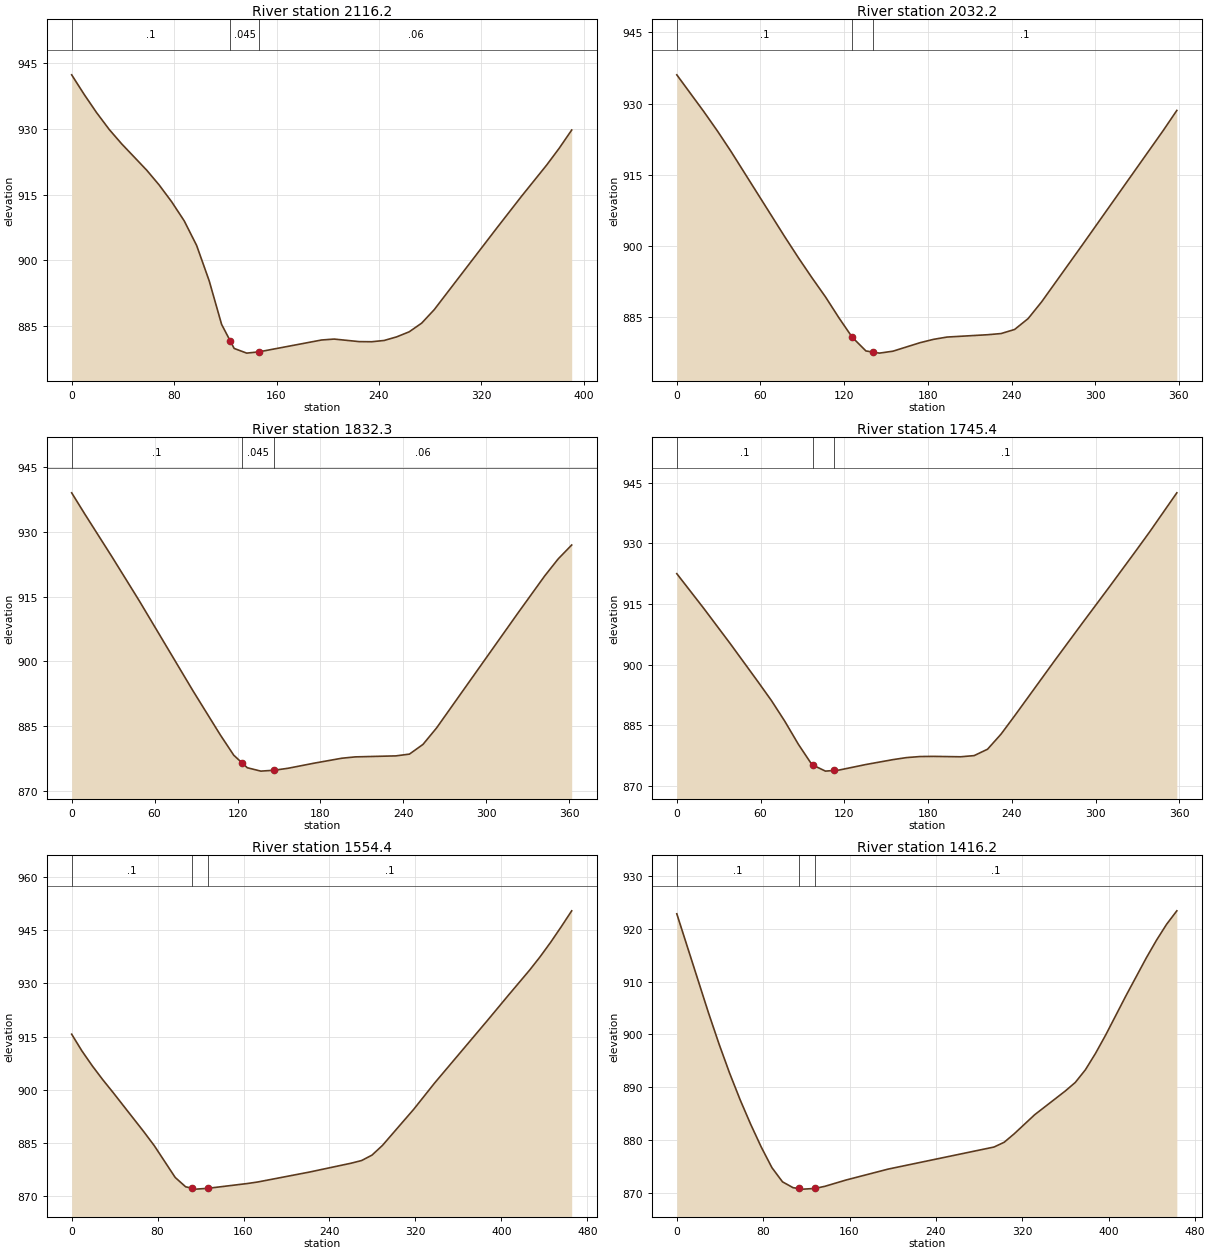
Type RM Length L Ch R = 1 ,2116.2  ,81.1,83.9,86.7
XS GIS Cut Line= 2
     1666596.172      312195.775     1666876.277       312467.82
#Sta/Elev= 30
       0  942.39     9.8   937.9    19.5  933.74    29.3  929.92      39  926.64
    58.6  920.61    68.3  917.24    78.1  913.39    87.9  909.03    97.6  903.41
   107.4  895.34   117.1  885.38  123.95881.5426   126.9  879.89   136.7  878.82
   146.4  879.12   195.2  881.82     205  882.03   224.5  881.45   234.3  881.42
     244  881.71   253.8  882.53   263.6  883.69   273.3  885.66   283.1  888.73
   331.9  907.35   351.4  914.68     371   921.8   380.7   925.6   390.5  929.78
#Mann= 3 , 0 , 0
       0      .1       0  123.95    .045       0   146.4     .06       0
Bank Sta=123.95,146.4
XS Rating Curve= 0 ,0
Exp/Cntr=0.3,0.1

Type RM Length L Ch R = 1 ,2032.2  ,201.9,199.9,197.8
XS GIS Cut Line= 2
     1666561.242      312256.317     1666797.015      312526.347
#Sta/Elev= 25
       0  936.05    19.4  928.28    29.1  924.22    38.8  919.92    77.5  901.85
    87.2  897.46    96.9  893.25   106.6  889.21   116.3  884.77   125.8  880.69
   135.6  877.81   140.8  877.56   145.3  877.35     155  877.76   174.4  879.55
   184.1  880.26   193.8  880.74   222.8  881.23   232.5  881.48   242.2  882.34
   251.9  884.64   261.6  888.18   290.7  900.15   348.8  924.33   358.5  928.54
#Mann= 3 , 0 , 0
       0      .1       0   125.8    .045       0   140.8      .1       0
Bank Sta=125.8,140.8
XS Rating Curve= 0 ,0
Exp/Cntr=0.3,0.1

Type RM Length L Ch R = 1 ,1832.3  ,85.5,86.9,88.3
XS GIS Cut Line= 2
     1666414.808      312373.108     1666648.565      312649.184
#Sta/Elev= 23
       0  938.95     9.8   933.9    29.3  924.11    48.9  914.02      88  893.11
   107.6  883.02   117.3  878.35   123.2  876.61   127.1  875.46   136.9  874.68
   146.6  874.89   156.4  875.33     176  876.55   195.5  877.66   205.3  877.97
   234.6   878.2   244.4  878.61   254.2  880.85     264  884.64   322.6  911.05
   342.2  919.73     352  923.68   361.8   926.9
#Mann= 3 , 0 , 0
       0      .1       0   123.2    .045       0   146.6     .06       0
Bank Sta=123.2,146.6
XS Rating Curve= 0 ,0
Exp/Cntr=0.3,0.1

Type RM Length L Ch R = 1 ,1745.4  ,184.3,191,197.7
XS GIS Cut Line= 2
     1666370.387      312446.121     1666596.084      312724.212
#Sta/Elev= 28
       0  922.49    19.4  913.86    38.7  904.98    58.1  895.77    67.8  891.08
    77.4  885.95    87.1  880.26    96.8  875.23    97.7  875.08   106.5  873.62
   112.7  873.79   116.2  873.88   135.5  875.26   154.9  876.47   164.6  876.97
   174.2  877.23   183.9  877.27   203.3  877.17     213  877.46   222.6  879.04
   232.3  882.79     242   887.3     271  901.12   290.4   910.2   309.8  919.18
   329.1  928.25   338.8  932.87   358.2   942.5
#Mann= 3 , 0 , 0
       0      .1       0    97.7    .045       0   112.7      .1       0
Bank Sta=97.7,112.7
XS Rating Curve= 0 ,0
Exp/Cntr=0.3,0.1

Type RM Length L Ch R = 1 ,1554.4  ,135.8,138.2,140.4
XS GIS Cut Line= 3
     1666230.203      312518.082     1666355.142      312800.203
     1666506.278      312842.522
#Sta/Elev= 28
       0  915.66     9.6  910.93    19.3  906.71    28.9  902.87    38.6  899.23
    67.5  888.07    77.1  884.19    96.4  875.32   106.1   872.7   111.6  872.32
   115.7  872.04   126.6  872.26   163.9  873.63   173.6  874.07   221.8  876.87
   260.3  879.35     270   880.1   279.6  881.62   289.3  884.34   318.4  894.51
     338  901.96     387  919.51   406.6  926.64   426.3   933.7   436.1  937.47
   445.9  941.54   455.7  945.89   465.5   950.4
#Mann= 3 , 0 , 0
       0      .1       0   111.6    .045       0   126.6      .1       0
Bank Sta=111.6,126.6
XS Rating Curve= 0 ,0
Exp/Cntr=0.3,0.1

Type RM Length L Ch R = 1 ,1416.2  ,160.6,162.4,164.3
XS GIS Cut Line= 3
      1666117.69      312573.776     1666208.649      312853.123
     1666208.649      313022.396
#Sta/Elev= 30
       0  922.82    29.4  904.06    39.2  898.15      49  892.64    58.8  887.58
    68.6  882.94    78.3  878.68    88.1  874.82    97.9  872.14   107.7  871.03
   112.9  870.89   117.5  870.76   127.9  870.89   137.1  871.29   156.7  872.48
   195.8  874.55   293.8  878.72   303.2  879.62   312.6  881.24   331.4  884.82
   359.6  889.28     369  890.92   378.4  893.32   387.8  896.43   397.2   899.9
     416  907.33   434.8  914.47   444.2   917.8   453.6  920.83   463.1  923.38
#Mann= 3 , 0 , 0
       0      .1       0   112.9    .045       0   127.9      .1       0
Bank Sta=112.9,127.9
XS Rating Curve= 0 ,0
Exp/Cntr=0.3,0.1

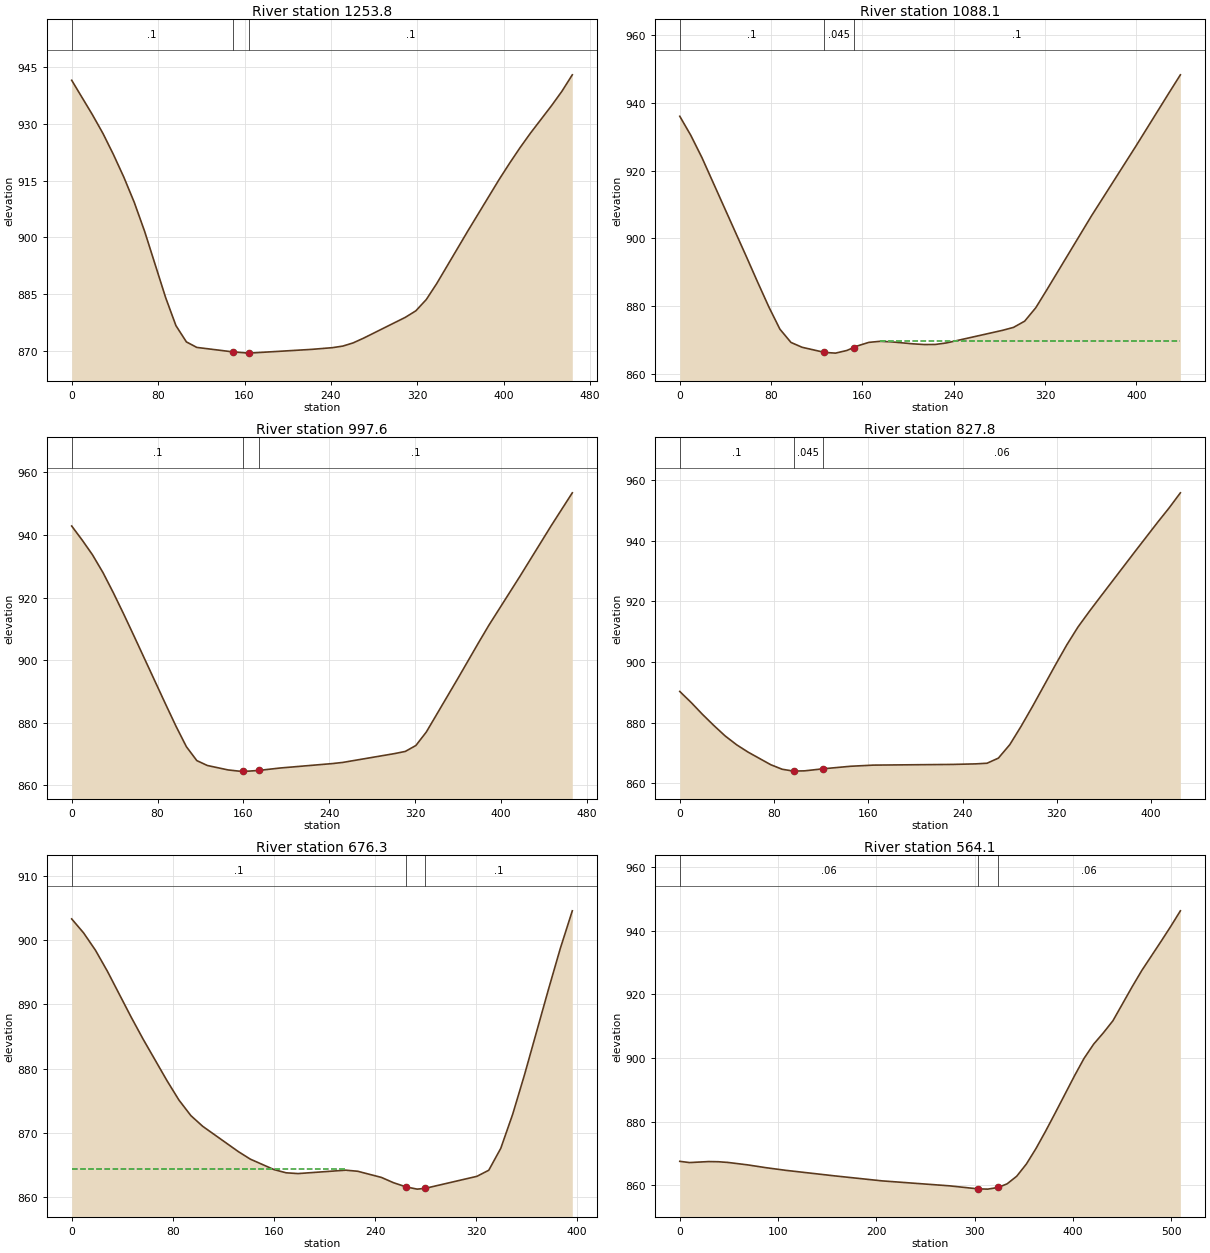
Type RM Length L Ch R = 1 ,1253.8  ,166.9,165.7,167.4
XS GIS Cut Line= 2
     1665982.179      312613.028      1666087.01      313064.393
#Sta/Elev= 30
       0  941.49    19.3  932.34      29  927.42    38.6   921.9    48.3  915.88
    57.9  909.26    67.6  901.52    86.9  884.15    96.5  876.69   106.2  872.39
   115.8  870.94   149.1  869.76   164.1  869.43     222  870.42   241.3  870.87
     251  871.29   260.6  872.14   270.3   873.4   308.9  878.89   318.6  880.61
   328.2  883.57   337.9   887.8   366.8  901.74   395.8  915.35   405.5  919.65
   415.1  923.72   424.8  927.58   444.1  934.76   453.7  938.55   463.4  942.93
#Mann= 3 , 0 , 0
       0      .1       0   149.1    .045       0   164.1      .1       0
Bank Sta=149.1,164.1
XS Rating Curve= 0 ,0
Exp/Cntr=0.3,0.1

Type RM Length L Ch R = 1 ,1088.1  ,92.6,90.5,88.3
XS GIS Cut Line= 2
      1665833.16      312669.189     1665931.902      313096.401
#Sta/Elev= 30
       0  936.02     9.7  930.37    19.5  923.77    58.5  894.52    68.2  887.13
      78  879.84    87.7  873.27    97.4  869.35   107.2  867.92   126.7  866.42
   136.4   866.2   146.2  866.97   152.2  867.82   155.9  868.35   165.6  869.37
   175.4  869.68   185.1  869.53   204.6  868.93   214.4  868.73   224.1  868.76
   233.8  869.22   282.6  872.91   292.3  873.78   302.1  875.62   311.8  879.56
   321.6  884.91   360.5  906.59   399.5   927.2   428.7     943   438.5  948.23
#Mann= 3 , 0 , 0
       0      .1       0   126.7    .045       0   152.2      .1       0
#XS Ineff= 2 , 0
                          175.35          869.92
Permanent Ineff=
       F       F
Bank Sta=126.7,152.2
XS Rating Curve= 0 ,0
Exp/Cntr=0.3,0.1

Type RM Length L Ch R = 1 ,997.6   ,176.5,169.8,163.1
XS GIS Cut Line= 2
     1665727.642      312677.396     1665873.769      313120.496
#Sta/Elev= 30
       0  942.83     9.7  938.38    19.4  933.63    29.2  927.94    38.9  921.47
    48.6  914.62    58.3  907.55    87.5  885.97    97.2  878.92   106.9  872.37
   116.6  867.94   126.4  866.37   145.8  864.95   155.5  864.58   159.8  864.58
   165.2  864.57   174.8  864.81   194.4  865.57     243  866.98   252.7  867.35
   301.3  870.19     311  870.87   320.8  872.75   330.5  877.04   359.6  893.96
   379.1  905.51   388.8  911.13     418  926.89   447.1  943.02   466.6  953.43
#Mann= 3 , 0 , 0
       0      .1       0   159.8    .045       0   174.8      .1       0
Bank Sta=159.8,174.8
XS Rating Curve= 0 ,0
Exp/Cntr=0.3,0.1

Type RM Length L Ch R = 1 ,827.8   ,153.4,151.5,149.6
XS GIS Cut Line= 2
     1665560.384      312810.396     1665806.233      313157.002
#Sta/Elev= 30
       0  890.33     9.7  886.68    19.3  882.77      29  879.08    38.6  875.64
    48.3  872.74      58  870.33    77.3  866.17    86.9  864.69    96.6  864.07
   106.2  864.17   121.5  864.83   144.9  865.67   164.2  866.05   231.8  866.28
   251.1  866.46   260.8  866.67   270.4  868.35   280.1  872.79   289.7  878.84
   299.4   885.4   318.7  898.98   328.4  905.62     338  911.58   347.7  916.75
   357.3  921.67   386.3   936.4   405.6  946.09   415.3   950.8   424.9   955.8
#Mann= 3 , 0 , 0
       0      .1       0    96.6    .045       0   121.5     .06       0
Bank Sta=96.6,121.5
XS Rating Curve= 0 ,0
Exp/Cntr=0.3,0.1

Type RM Length L Ch R = 1 ,676.3   ,115.7,112.2,108.8
XS GIS Cut Line= 3
     1665485.473      312796.261     1665535.852        312987.7
     1665672.882      313130.776
#Sta/Elev= 30
       0  903.29     9.4  901.12    18.8  898.42    28.3  895.13    47.1  887.99
    56.6  884.55    75.4  878.12    84.8  875.12    94.3  872.68   103.7  871.01
     132  867.06   141.4   865.9   160.2  864.27   169.7  863.78   179.1  863.66
   216.8  864.19   226.3  864.02   245.1  863.06   254.6  862.24   264.7  861.58
   273.4  861.24   279.7  861.36   320.6  863.23     330  864.18   339.5  867.59
   348.9  872.88   358.3  879.05   377.2   892.3   386.6  898.69   396.1  904.55
#Mann= 3 , 0 , 0
       0      .1       0   264.7    .045       0   279.7      .1       0
#XS Ineff= 2 , 0
           216.9  864.41
Permanent Ineff=
       F       F
Bank Sta=264.7,279.7
XS Rating Curve= 0 ,0
Exp/Cntr=0.3,0.1

Type RM Length L Ch R = 1 ,564.1   ,135.4,135.1,134.7
XS GIS Cut Line= 2
      1665300.43       312925.26     1665677.263      313267.835
#Sta/Elev= 30
       0  867.49     9.8   867.1    29.4  867.41    39.2  867.36      49  867.14
    68.6  866.39    88.1  865.47   107.7  864.66   156.7  862.94   205.7  861.34
   274.2  859.78   303.6  858.82   313.4  858.74   323.8  859.26     333   860.4
   342.8   862.8   352.6  866.63   362.4  871.52   372.2  876.99     382  882.73
   401.5  894.36   411.3   899.9   421.1  904.39   430.9  907.91   440.7  911.75
   460.3  922.47   470.1  927.58   489.7  936.75   499.5  941.43   509.3  946.33
#Mann= 3 , 0 , 0
       0     .06       0   303.6    .045       0   323.8     .06       0
Bank Sta=303.6,323.8
XS Rating Curve= 0 ,0
Exp/Cntr=0.3,0.1

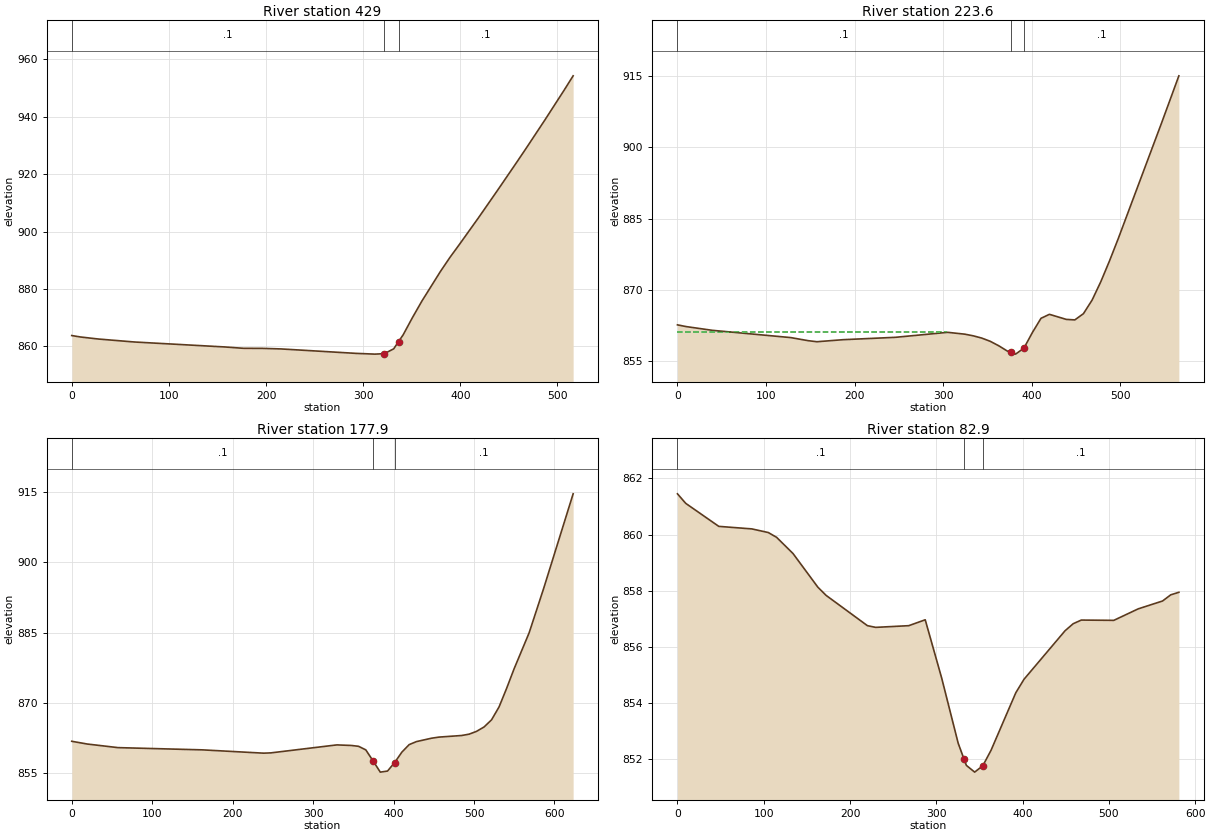
Type RM Length L Ch R = 1 ,429     ,182,205.4,227.4
XS GIS Cut Line= 4
     1665338.265      313001.806     1665353.218      313139.187
     1665548.542      313312.081     1665655.082      313360.678
#Sta/Elev= 27
       0  863.73     9.2  863.22    27.6  862.51    64.5  861.48   157.5  859.75
   176.8  859.28   196.2  859.26   215.5  859.06   292.8  857.51   312.1  857.25
   321.4  857.41   321.8  857.42   331.4   859.1   336.4  861.61   341.1  863.96
   350.7  869.99   360.4  875.74   379.7  886.18   389.4  891.03     399  895.48
   418.6  904.77   438.1  914.28   457.6  923.94   467.4  928.86   486.9  938.84
   506.4  949.07   516.1   954.3
#Mann= 3 , 0 , 0
       0      .1       0   321.4    .045       0   336.4      .1       0
Bank Sta=321.4,336.4
XS Rating Curve= 0 ,0
Exp/Cntr=0.3,0.1

Type RM Length L Ch R = 1 ,223.6   ,45.4,45.7,47.3
XS GIS Cut Line= 4
     1665336.396      313022.366     1665358.825      313336.379
     1665342.938      313469.087     1665418.637      313558.805
#Sta/Elev= 30
       0  862.63     9.8  862.27    39.4  861.48   127.9  859.95   147.6   859.3
   157.4  859.08   186.9  859.51     246  860.01     305  861.06   324.4  860.67
   333.9  860.32   343.4  859.85     353  859.17   362.6  858.23   372.1  857.14
     376  856.86   381.6  856.47     391  857.72   400.7  861.06   410.3  864.01
   419.8  864.85   438.9  863.78   448.5  863.68   458.2  864.99     468  867.86
   477.8  871.72   487.6  876.09   497.4  880.75   546.3   905.1   565.9  915.07
#Mann= 3 , 0 , 0
       0      .1       0     376    .045       0     391      .1       0
#XS Ineff= 2 , 0
          304.23  861.18
Permanent Ineff=
       F       F
Bank Sta=376,391
XS Rating Curve= 0 ,0
Exp/Cntr=0.3,0.1

Type RM Length L Ch R = 1 ,177.9   ,74.4,95,115.8
XS GIS Cut Line= 6
      1665315.27      313021.879     1665317.705      313241.989
      1665316.77      313351.332     1665298.079      313448.527
     1665270.976      313585.908     1665286.864      313638.243
#Sta/Elev= 30
       0  861.85    19.1  861.27    57.4   860.5   162.7  860.02   238.4  859.32
   247.5  859.38   329.5  861.08   347.5  860.96   356.5  860.78   365.5  860.02
   374.6  857.65   383.5  855.28   392.5  855.51   401.4  857.33   410.4  859.55
   419.4  861.14   428.4  861.78   447.1   862.5   456.4  862.74   484.5  863.08
   493.8  863.36   503.1  863.96   512.5   864.9   521.8  866.42   531.1  869.16
   540.5  873.11   549.8  877.28   568.5  884.95   586.7  894.48   623.2  914.56
#Mann= 3 , 0 , 0
       0      .1       0   374.6    .045       0   401.4      .1       0
Bank Sta=374.6,401.4
XS Rating Curve= 0 ,0
Exp/Cntr=0.3,0.1

Type RM Length L Ch R = 1 ,82.9    ,90.1,82.9,75.6
XS GIS Cut Line= 4
     1665308.759      313024.483     1665290.602      313311.146
     1665156.267      313383.556     1665170.044      313524.227
#Sta/Elev= 30
       0  861.45     9.6  861.11    47.9  860.29    86.2   860.2   105.3  860.07
   114.9   859.9     134  859.32   162.8  858.12   172.3  857.83   220.2  856.75
   229.8  856.69   268.1  856.75   287.2  856.96   306.3  854.88   325.4  852.56
   332.1     852   334.9  851.77   344.5  851.53     354  851.76   363.5  852.31
   392.2  854.36   401.7  854.84   449.3  856.57   458.7  856.82   468.1  856.95
   505.8  856.94   534.1  857.35   562.3  857.63   571.8  857.85   581.2  857.94
#Mann= 3 , 0 , 0
       0      .1       0   332.1    .045       0     354      .1       0
Bank Sta=332.1,354
XS Rating Curve= 0 ,0
Exp/Cntr=0.3,0.1

Chan Stop Cuts=-1
Use User Specified Reach Order=0
Composite Channel Slope=5